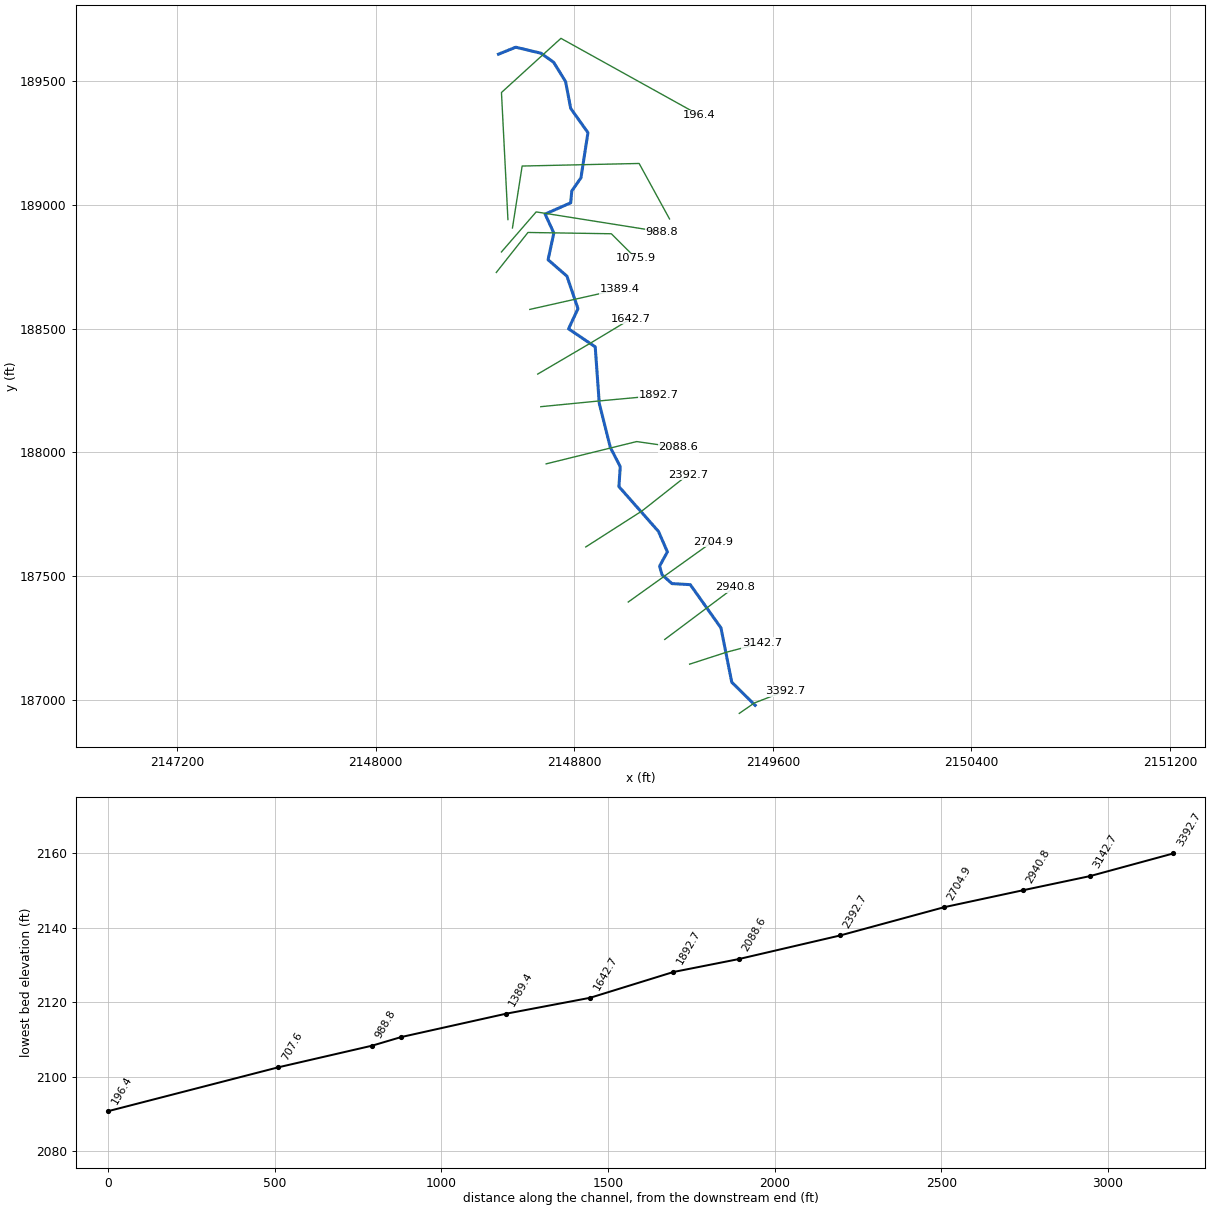
--- POTTSCKT1.prj (project) ---

Proj Title=POTTSCKT1
Current Plan=p01
Default Exp/Contr=0,0
English Units
Geom File=g01
Flow File=f01
Plan File=p01
BEGIN DESCRIPTION:
END DESCRIPTION:
DSS Export Rating Curves= 0
DSS Export Rating Curve Sorted= 0
DSS Export Volume Flow Curves= 0
DXF OffsetX= 0
DXF OffsetY= 0
DXF ScaleX= 0
DXF ScaleY= 0

--- POTTSCKT1.p01 (plan) ---

Plan Title=Floodplain
Program Version=4.00
Geom File=g01
Flow File=f01
K Sum by GR=0
Std Step Tol=0.01
Critical Tol=0.01
Num of Std Step Trials=20
Max Error Tol=0.3
Flow Tol Ratio=0.001
Split Flow NTrial=30
Split Flow Tol=0.02
Split Flow Ratio=0.02
Log Output Level=0
Friction Slope Method=1
Unsteady Friction Slope Method=2
Unsteady Bridges Friction Slope Method=1
Global Log Level=0
CheckData=False
Run HTab=0
Run UNet=0
Run PostProcess=0
UNET Theta=0
UNET Theta Warmup=0
UNET ZTol=0
UNET ZSATol=0
UNET MxIter=0
UNET MaxInSteps=0
UNET DtIC=0
UNET DtMin=0
UNET MaxCRTS=0
UNET WFStab=0
UNET SFStab=0
UNET WFX=0
UNET SFX=0
UNET DSS MLevel=0
UNET DZMax Abort=0
UNET Convert EG Bridges=0
UNET Use Existing IB Tables=0
UNET Froude Limit=0
UNET Froude Power=0
Write IC File=0
Echo Input=False
Echo Output=False
Write Detailed=0

--- POTTSCKT1.f01 (steady flow) ---

Flow Title=2010 USGS WV Regression Equation
Program Version=4.00
Number of Profiles=1
Profile Names=P100yr
River Rch & RM=POTTSCKT1,Main      ,3392.7
530.0007
River Rch & RM=POTTSCKT1,Main      ,196.4
563.2220
River Rch & RM=POTTSCKT1,Main      ,196.4
560.3150
Boundary for River Rch & Prof#=POTTSCKT1,Main      ,1
Up Type=0
Dn Type=3
Dn Slope=0.022965

--- POTTSCKT1.g01 (geometry) ---

Geom Title=LiDAR
Program Version=4.10

River Reach=POTTSCKT1       ,Main
Reach XY= 30
     2149528.661         186979.      2149434.26      187072.316
     2149390.857        187291.5     2149267.159      187466.196
     2149193.375      187470.537     2149153.227      187506.344
     2149143.461      187541.066     2149174.929      187598.575
     2149139.121       187681.04     2148979.616      187862.247
     2148985.042      187942.542     2148944.894      188020.667
     2148900.406      188198.618      2148884.13      188426.483
     2148776.708      188499.182     2148814.686      188580.563
     2148770.197      188711.856     2148694.243      188778.045
     2148717.377      188886.035     2148682.307      188962.507
     2148785.389       189008.08     2148789.729      189055.823
     2148826.621      189108.991     2148854.833      189291.283
     2148785.323       189389.39     2148764.772      189497.446
     2148716.595      189575.571      2148665.38       189612.03
     2148563.817      189636.335     2148494.493      189608.167

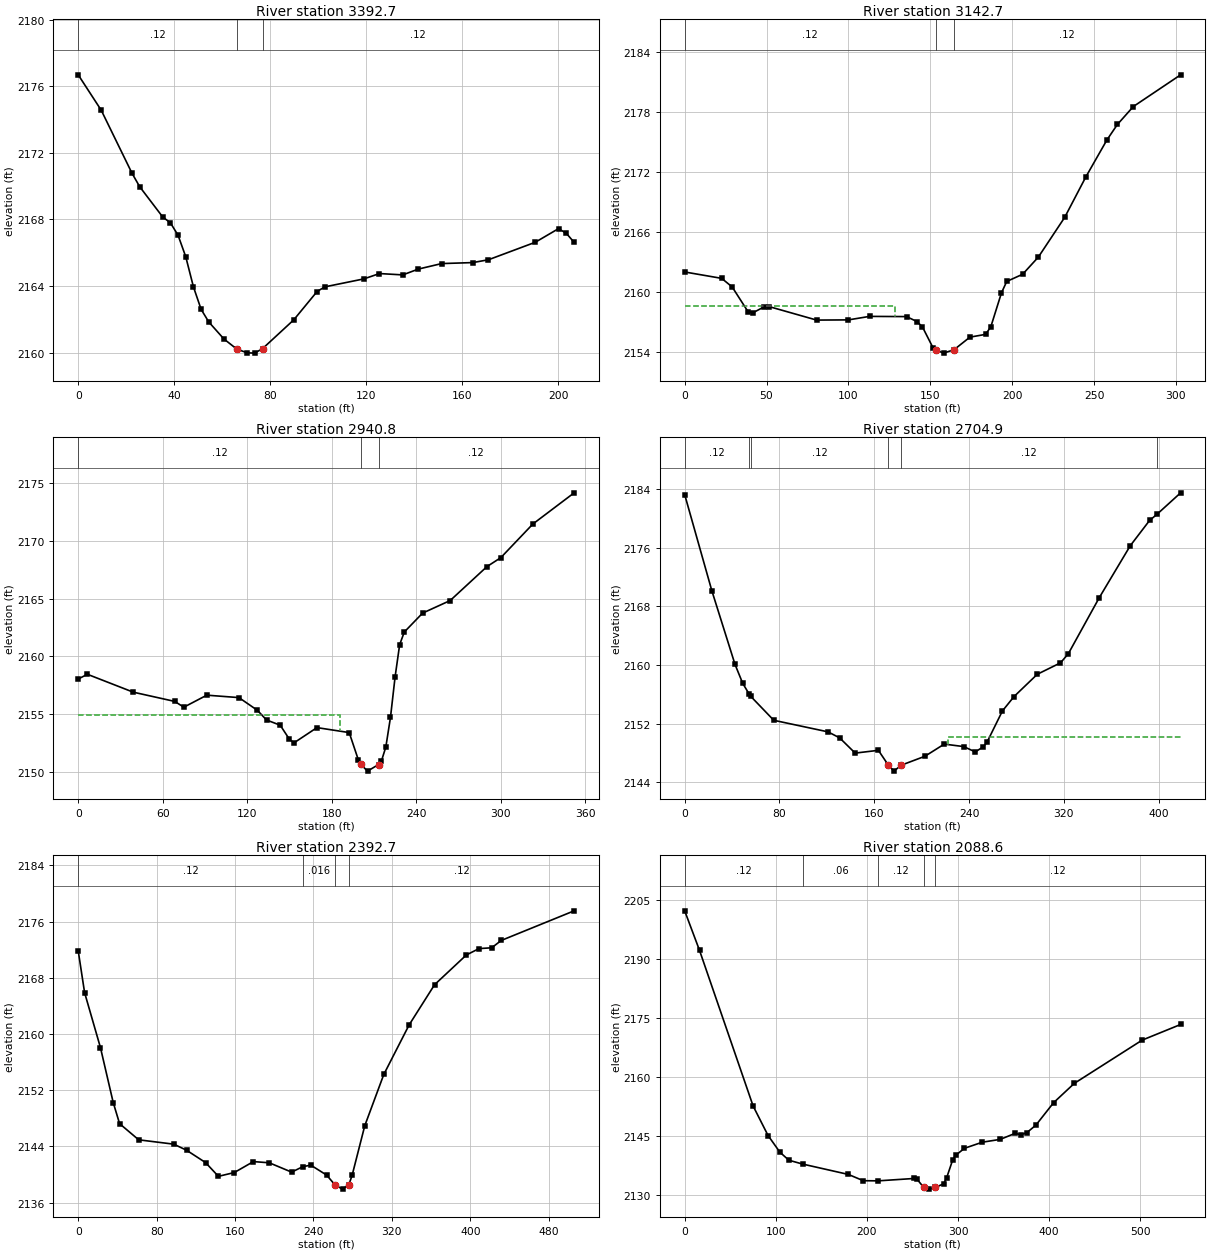
Type RM Length L Ch R = 1 ,3392.7  ,256.7,250,247.1
XS GIS Cut Line= 3
     2149464.516      186946.519     2149525.017      186988.313
     2149648.935      187036.803
#Sta/Elev= 30
       0 2176.69     9.6 2174.56    22.4 2170.78    25.6 2169.97    35.2 2168.15
    38.4  2167.8    41.6 2167.05    44.8 2165.76      48 2163.95    51.2  2162.6
    54.4 2161.84    60.7 2160.82      66 2160.22    70.3 2159.99    73.5 2159.97
    76.8 2160.24    89.8 2161.97    99.5 2163.67   102.7 2163.95     119 2164.43
   125.5 2164.75   135.2 2164.67   141.7 2165.02   151.4 2165.35   164.4 2165.41
   170.9 2165.58   190.4 2166.63   200.1 2167.45   203.4 2167.16   206.6 2166.62
#Mann= 3 ,-1 , 0
       0     .12       0      66    .045       0    76.8     .12       0
Bank Sta=66,76.8
XS Rating Curve= 0 ,0
Exp/Cntr=0.3,0.1

Type RM Length L Ch R = 1 ,3142.7  ,194.3,201.9,210.6
XS GIS Cut Line= 3
      2149264.59      187145.266     2149414.953      187194.031
     2149555.069      187230.737
#Sta/Elev= 30
       0 2162.01    22.6 2161.37      29 2160.51    38.7 2158.03    41.9 2157.94
    48.4 2158.51    51.6 2158.54    80.6 2157.19     100 2157.21   112.9 2157.56
   135.5 2157.54   141.9 2157.04   145.2 2156.51   151.6 2154.44  153.252154.218
   158.1 2153.88   164.5 2154.22   174.2 2155.48   183.8 2155.76     187 2156.53
   193.5 2159.93   196.7 2161.06   206.4 2161.78     216  2163.5   232.1 2167.48
     245 2171.53   257.9 2175.24   264.3 2176.79     274 2178.58   302.9 2181.76
#Mann= 3 ,-1 , 0
       0     .12       0  153.25    .045       0   164.5     .12       0
#XS Ineff= 2 , 0
          128.22 2158.63
Permanent Ineff=
       F       F
Bank Sta=153.25,164.5
XS Rating Curve= 0 ,0
Exp/Cntr=0.3,0.1

Type RM Length L Ch R = 1 ,2940.8  ,235.2,235.9,235.4
XS GIS Cut Line= 2
     2149164.249      187245.015     2149445.838      187456.419
#Sta/Elev= 30
       0 2158.04     6.5 2158.45    39.1  2156.9    68.5  2156.1      75  2155.6
    91.3 2156.64   114.1 2156.43   127.2 2155.33   133.7 2154.49   143.4 2154.04
     150 2152.81   153.2 2152.51   169.5 2153.83   192.4  2153.4   198.9 2151.03
  200.622150.648   205.4 2150.06   213.2 2150.63   215.2 2150.91   218.4 2152.15
   221.7 2154.72     225 2158.25   228.2 2161.01   231.5 2162.11   244.5 2163.75
   264.1 2164.84   290.2 2167.78     300 2168.55   322.8 2171.47   352.1 2174.17
#Mann= 3 ,-1 , 0
       0     .12       0  200.62    .045       0   213.2     .12       0
#XS Ineff= 2 , 0
          186.17 2154.94
Permanent Ineff=
       F       F
Bank Sta=200.62,213.2
XS Rating Curve= 0 ,0
Exp/Cntr=0.3,0.1

Type RM Length L Ch R = 1 ,2704.9  ,311.9,312.3,312.5
XS GIS Cut Line= 2
      2149017.28      187396.211     2149357.497      187640.072
#Sta/Elev= 30
       0 2183.27    22.9 2170.16    42.5 2160.08      49  2157.5   54.152156.113
    55.82155.723    75.2 2152.46     121 2150.88   130.8 2150.06   143.9 2147.98
   163.5 2148.36  171.612146.405   176.6 2145.52   182.8 2146.33   202.8 2147.55
   219.1 2149.21   235.5 2148.87   245.3 2148.14   251.8 2148.82   255.1 2149.44
   268.2 2153.74     278  2155.7   297.6 2158.74   317.2  2160.3   323.8 2161.54
   349.9 2169.19   376.1 2176.29   392.4 2179.74  398.532180.562   418.6 2183.51
#Mann= 6 ,-1 , 0
       0     .12       0   54.15     .06       0    55.8     .12       0
  171.61    .045       0   182.8     .12       0  398.53     .06       0
#XS Ineff= 2 , 0
                          222.39         2150.14
Permanent Ineff=
       F       F
Bank Sta=171.61,182.8
XS Rating Curve= 0 ,0
Exp/Cntr=0.3,0.1

Type RM Length L Ch R = 1 ,2392.7  ,310.7,304.1,294
XS GIS Cut Line= 3
      2148845.96      187618.398     2149072.892      187764.066
     2149258.221      187910.581
#Sta/Elev= 30
       0 2171.85     6.5  2165.9    22.7 2158.06    35.7 2150.25    42.2 2147.24
    61.7 2144.94    97.5 2144.32   110.5 2143.46     130 2141.69     143 2139.74
   159.2 2140.28   178.7 2141.84   194.9 2141.67   217.7 2140.34   228.92141.102
   237.2 2141.34   253.4 2139.92   262.2 2138.48   269.7 2137.92   276.1 2138.57
   279.4 2139.88   292.3 2146.94   311.7 2154.24   337.6 2161.31   363.5 2167.02
   395.9 2171.25   408.8 2172.16   421.8 2172.28   431.5 2173.32   505.9 2177.54
#Mann= 4 ,-1 , 0
       0     .12       0   228.9    .016       0   262.2    .045       0
   276.1     .12       0
Bank Sta=262.2,276.1
XS Rating Curve= 0 ,0
Exp/Cntr=0.3,0.1

Type RM Length L Ch R = 1 ,2088.6  ,199,195.9,192.6
XS GIS Cut Line= 3
     2148686.523      187954.009     2149051.209      188044.037
      2149218.03      188020.095
#Sta/Elev= 30
       0  2202.2    16.3 2192.16    75.1 2152.67    91.5 2145.18   104.5 2140.95
   114.3 2138.92  129.472137.935   179.6 2135.31     196 2133.72  212.28 2133.68
   251.5 2134.28   254.8 2134.14  262.332132.005   267.8 2131.58   275.1    2132
   284.2 2132.95   287.4 2134.42     294 2138.94   297.2 2140.13     307 2141.94
   326.6 2143.49   346.2  2144.2   362.6 2145.73   369.1 2145.38   375.6 2145.94
   385.4 2147.82   404.8 2153.51   427.5 2158.41     502 2169.39   544.2 2173.36
#Mann= 5 ,-1 , 0
       0     .12       0  129.47     .06       0  212.28     .12       0
  262.33    .045       0   275.1     .12       0
Bank Sta=262.33,275.1
XS Rating Curve= 0 ,0
Exp/Cntr=0.3,0.1

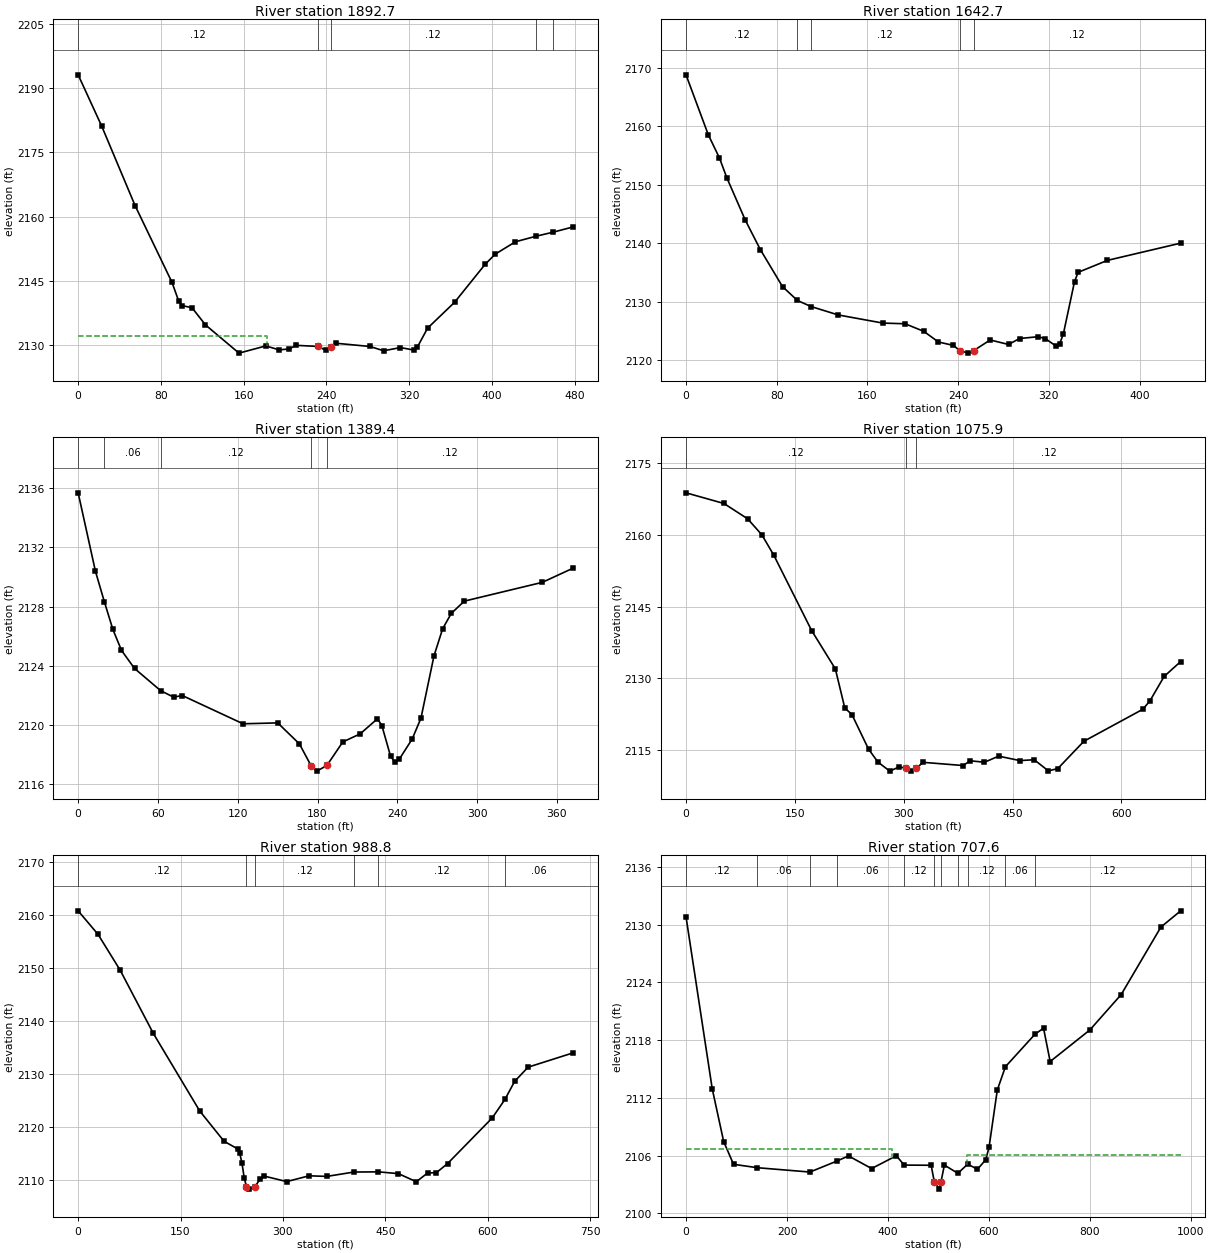
Type RM Length L Ch R = 1 ,1892.7  ,239.4,250,259.3
XS GIS Cut Line= 3
     2148664.849      188184.841     2148900.192       188208.02
     2149140.913      188230.226
#Sta/Elev= 30
       0  2193.1    22.7 2181.16    55.1 2162.53    90.7 2144.65    97.2 2140.28
   100.4 2139.22   110.1  2138.7   123.1  2134.7   155.5 2128.11   181.4 2129.79
   194.4 2128.87   204.1 2129.09   210.6 2129.93  231.672129.676   239.8 2128.73
     244 2129.62   249.6 2130.41   282.2 2129.66   295.3 2128.66   311.6 2129.41
   324.7 2128.82     328 2129.55   337.8 2133.94   363.9 2139.98   393.3 2148.81
   403.1 2151.21   422.7 2154.11  442.78 2155.42  458.582156.319   478.2 2157.56
#Mann= 5 ,-1 , 0
       0     .12       0  231.67    .045       0     244     .12       0
  442.78     .06       0  458.58     .12       0
#XS Ineff= 2 , 0
          182.15 2132.16
Permanent Ineff=
       F       F
Bank Sta=231.67,244
XS Rating Curve= 0 ,0
Exp/Cntr=0.3,0.1

Type RM Length L Ch R = 1 ,1642.7  ,259.9,253.3,243.8
XS GIS Cut Line= 3
     2148652.489      188316.468     2148866.985      188442.632
     2149027.428      188539.454
#Sta/Elev= 30
       0 2168.77    19.6 2158.54    29.5 2154.54      36 2151.16    52.4 2143.87
    65.5  2138.9    85.1 2132.55   98.212130.189  110.162129.153   134.2 2127.71
   173.5 2126.32   193.2  2126.2   209.6 2124.91   222.6 2123.08   235.8  2122.5
   241.3 2121.62   248.8 2121.18  253.792121.622   268.2 2123.43   284.4 2122.66
   294.1 2123.68   310.2 2123.98   316.7 2123.68   326.4 2122.37   329.6 2122.82
   332.8 2124.51   342.6 2133.42   345.8    2135   371.6 2137.04   436.2 2139.99
#Mann= 5 ,-1 , 0
       0     .12       0   98.21     .06       0  110.16     .12       0
   241.3    .045       0  253.79     .12       0
Bank Sta=241.3,253.79
XS Rating Curve= 0 ,0
Exp/Cntr=0.3,0.1

Type RM Length L Ch R = 1 ,1389.4  ,319.8,313.5,305.3
XS GIS Cut Line= 2
     2148620.558      188577.574     2148983.426      188659.353
#Sta/Elev= 30
       0 2135.69      13 2130.39   19.672128.339    26.1 2126.46    32.6 2125.04
    42.4 2123.82   62.032122.319    71.8 2121.88    78.3 2121.99     124 2120.08
   150.1 2120.14   166.4 2118.72   175.2 2117.24   179.5 2116.88  187.062117.262
     199 2118.85   212.1  2119.4   225.1 2120.42   228.4 2119.96   234.9  2117.9
   238.2 2117.48   241.4 2117.67   251.2 2119.05   257.8 2120.46   267.6 2124.67
   274.1  2126.5   280.6 2127.54   290.4 2128.37   349.1 2129.64     372 2130.59
#Mann= 5 ,-1 , 0
       0     .12       0   19.67     .06       0   62.03     .12       0
   175.2    .045       0  187.06     .12       0
Bank Sta=175.2,187.06
XS Rating Curve= 0 ,0
Exp/Cntr=0.3,0.1

Type RM Length L Ch R = 1 ,1075.9  ,89.7,87,94
XS GIS Cut Line= 4
     2148485.563      188726.825     2148613.167      188888.283
     2148949.105      188883.075     2149048.063      188784.116
#Sta/Elev= 30
       0 2168.79    52.3 2166.56    84.9 2163.36   104.5 2160.02   120.9 2155.78
   173.1 2140.01   205.8 2131.99   218.8 2123.83   228.6 2122.46   251.5 2115.24
   264.5 2112.52   280.8 2110.63   293.9 2111.53   303.6 2111.22   310.2 2110.67
  317.582111.222   326.5 2112.47   381.9  2111.8   391.7 2112.79   411.3 2112.49
   430.9 2113.76   460.2 2112.83   479.8 2113.01   499.4 2110.68   512.4 2111.17
   548.3 2116.87   629.6 2123.56   639.4 2125.33   658.9 2130.42   681.7 2133.53
#Mann= 3 ,-1 , 0
       0     .12       0   303.6    .045       0  317.58     .12       0
Bank Sta=303.6,317.58
XS Rating Curve= 0 ,0
Exp/Cntr=0.3,0.1

Type RM Length L Ch R = 1 ,988.8   ,277.2,281.3,269.1
XS GIS Cut Line= 3
     2148506.288      188809.615     2148646.262      188971.291
     2149150.819      188890.996
#Sta/Elev= 30
       0 2160.78    29.2 2156.33    61.6 2149.58   110.2 2137.66   178.2 2123.04
   213.8 2117.34   233.5 2115.92   236.8 2115.07     240 2113.26   243.3 2110.46
   246.5 2108.81   249.9 2108.32   259.3 2108.79   266.2 2110.18   272.8 2110.77
   305.6 2109.74   338.3 2110.83   364.5 2110.72  404.072111.542  440.042111.575
   469.3 2111.24   495.5 2109.71   511.9 2111.35     525 2111.43   541.4 2113.15
   606.8 2121.75  625.332125.229   639.6 2128.64   659.3 2131.31   724.8 2133.99
#Mann= 6 ,-1 , 0
       0     .12       0   246.5    .045       0   259.3     .12       0
  404.07     .06       0  440.04     .12       0  625.33     .06       0
Bank Sta=246.5,259.3
XS Rating Curve= 0 ,0
Exp/Cntr=0.3,0.1

Type RM Length L Ch R = 1 ,707.6   ,494.5,511.2,527.9
XS GIS Cut Line= 4
     2148550.667      188906.512      2148589.73      189156.512
     2149061.084      189166.929      2149183.48       188942.97
#Sta/Elev= 30
       0 2130.81    51.9 2112.94    74.6 2107.45    94.1 2105.09  141.352104.735
  245.372104.285  298.782105.425   321.8 2105.96   367.6 2104.65   416.7 2105.98
  431.972105.009   485.5 2104.99  491.632103.296   501.9 2102.51   505.1  2103.3
   511.7 2105.01  538.462104.152  557.89 2105.11   577.2 2104.57   593.5 2105.56
   600.1 2106.84   616.5 2112.81  632.592115.231   691.42118.622   708.1 2119.23
   721.2 2115.77   799.8 2119.05   861.9 2122.73   940.5 2129.74   979.7 2131.43
#Mann= 11 ,-1 , 0
       0     .12       0  141.35     .06       0  245.37    .016       0
  298.78     .06       0  431.97     .12       0  491.63    .045       0
   505.1     .12       0  538.46     .06       0  557.89     .12       0
  632.59     .06       0   691.4     .12       0
#XS Ineff= 2 , 0
          408.06 2106.72  555.56         2106.09
Permanent Ineff=
       F       F
Bank Sta=491.63,505.1
XS Rating Curve= 0 ,0
Exp/Cntr=0.3,0.1

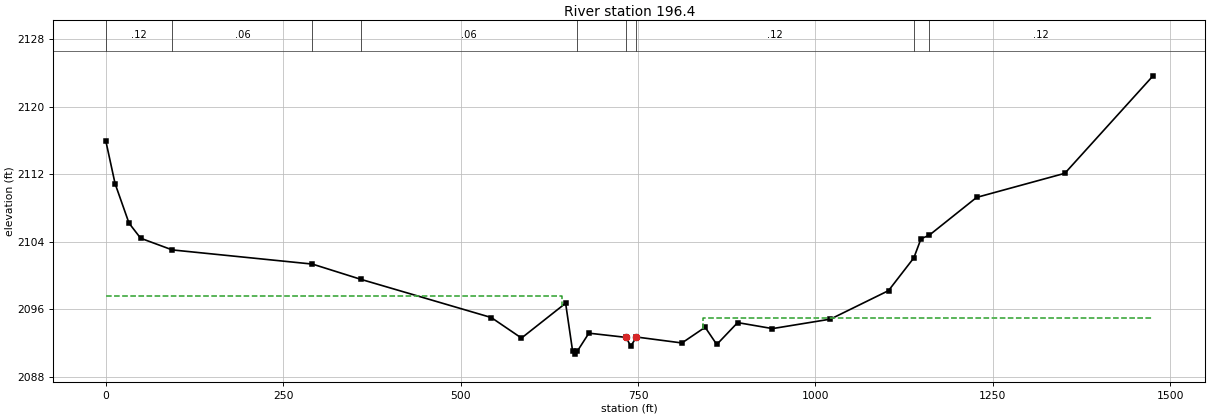
Type RM Length L Ch R = 1 ,196.4   ,168.5,196.3,222.1
XS GIS Cut Line= 4
     2148532.438      188940.366     2148506.397      189453.387
      2148745.98      189672.137     2149303.272      189362.241
#Sta/Elev= 30
       0 2115.95    13.1 2110.88    32.7 2106.21    49.1 2104.42   93.712103.037
   291.22101.361  359.162099.565   543.2 2095.04   585.8 2092.61     648 2096.73
   657.9 2091.04   661.2 2090.71  664.422091.052   680.8 2093.19   733.2 2092.69
   739.8 2091.65  747.812092.734   811.9 2092.03   844.6 2093.89     861 2091.85
   890.4 2094.44   939.5 2093.73  1021.2 2094.85    1103 2098.22 1138.722102.098
  1148.8 2104.36 1160.252104.765  1227.2 2109.25  1351.5  2112.1  1475.8 2123.63
#Mann= 9 ,-1 , 0
       0     .12       0   93.71     .06       0   291.2    .016       0
  359.16     .06       0  664.42     .12       0   733.2    .045       0
  747.81     .12       0 1138.72     .06       0 1160.25     .12       0
#XS Ineff= 2 , 0
          643.46 2097.62  841.69         2094.97
Permanent Ineff=
       F       F
Bank Sta=733.2,747.81
XS Rating Curve= 0 ,0
Exp/Cntr=0.3,0.1

Chan Stop Cuts=-1
Use User Specified Reach Order=0
Composite Channel Slope=5